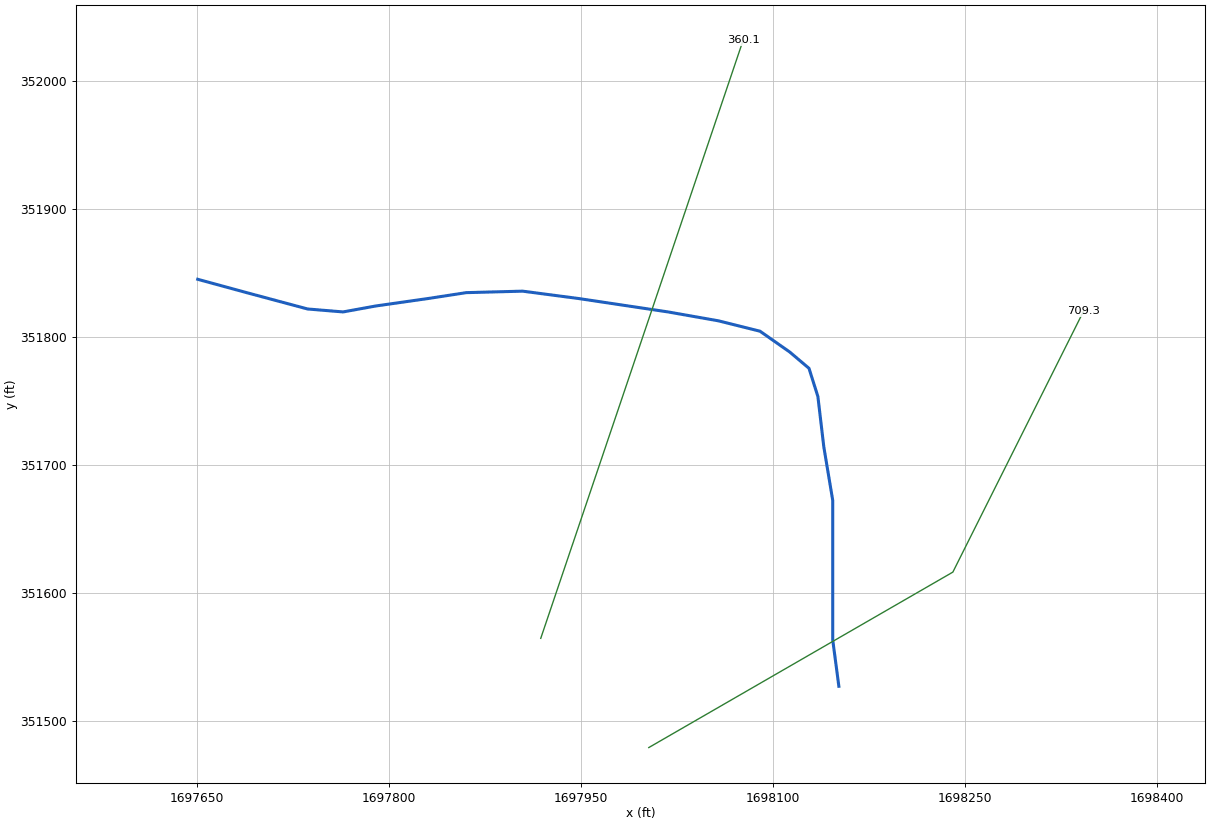
--- BIGCRK.prj (project) ---

Proj Title=BIGCRK
Current Plan=p01
Default Exp/Contr=0,0
English Units
Geom File=g01
Flow File=f01
Plan File=p01
BEGIN DESCRIPTION:
END DESCRIPTION:
DSS Export Rating Curves= 0
DSS Export Rating Curve Sorted= 0
DSS Export Volume Flow Curves= 0
DXF OffsetX= 0
DXF OffsetY= 0
DXF ScaleX= 0
DXF ScaleY= 0

--- BIGCRK.p01 (plan) ---

Plan Title=Floodplain
Program Version=4.00
Geom File=g01
Flow File=f01
K Sum by GR=0
Std Step Tol=0.01
Critical Tol=0.01
Num of Std Step Trials=20
Max Error Tol=0.3
Flow Tol Ratio=0.001
Split Flow NTrial=30
Split Flow Tol=0.02
Split Flow Ratio=0.02
Log Output Level=0
Friction Slope Method=1
Unsteady Friction Slope Method=2
Unsteady Bridges Friction Slope Method=1
Global Log Level=0
CheckData=False
Run HTab=0
Run UNet=0
Run PostProcess=0
UNET Theta=0
UNET Theta Warmup=0
UNET ZTol=0
UNET ZSATol=0
UNET MxIter=0
UNET MaxInSteps=0
UNET DtIC=0
UNET DtMin=0
UNET MaxCRTS=0
UNET WFStab=0
UNET SFStab=0
UNET WFX=0
UNET SFX=0
UNET DSS MLevel=0
UNET DZMax Abort=0
UNET Convert EG Bridges=0
UNET Use Existing IB Tables=0
UNET Froude Limit=0
UNET Froude Power=0
Write IC File=0
Echo Input=False
Echo Output=False
Write Detailed=0

--- BIGCRK.f01 (steady flow) ---

Flow Title=NFF Regression Equation
Program Version=4.10
Number of Profiles= 1
Profile Names=P100yr
River Rch & RM=BIGCRK,Main            ,709.3
927.2205
River Rch & RM=BIGCRK,Main            ,360.1
1225.039
Boundary for River Rch & Prof#=BIGCRK,Main            , 1
Up Type= 0
Dn Type= 1
Dn Known WS=800.31
DSS Import GetInterval= 0
DSS Import GetPeak= 0
DSS Import FillOption= 0

--- BIGCRK.g01 (geometry) ---

Geom Title=USGS 10m DEM
Program Version=4.10

River Reach=BIGCRK          ,Main
Reach XY= 21
     1698151.439      351527.006     1698146.648      351563.283
     1698146.648       351587.61     1698146.648       351632.79
     1698146.648      351672.177     1698139.697      351713.882
     1698135.064      351753.269     1698128.113      351775.279
     1698113.053      351788.022     1698089.884      351804.241
     1698057.448       351812.35      1698018.06        351819.3
     1697948.553      351829.726     1697904.532      351835.519
     1697860.511       351834.36     1697830.391      351829.726
     1697789.845      351823.934      1697764.36        351819.3
     1697736.557      351821.617     1697689.061       351834.36
     1697650.832      351844.786

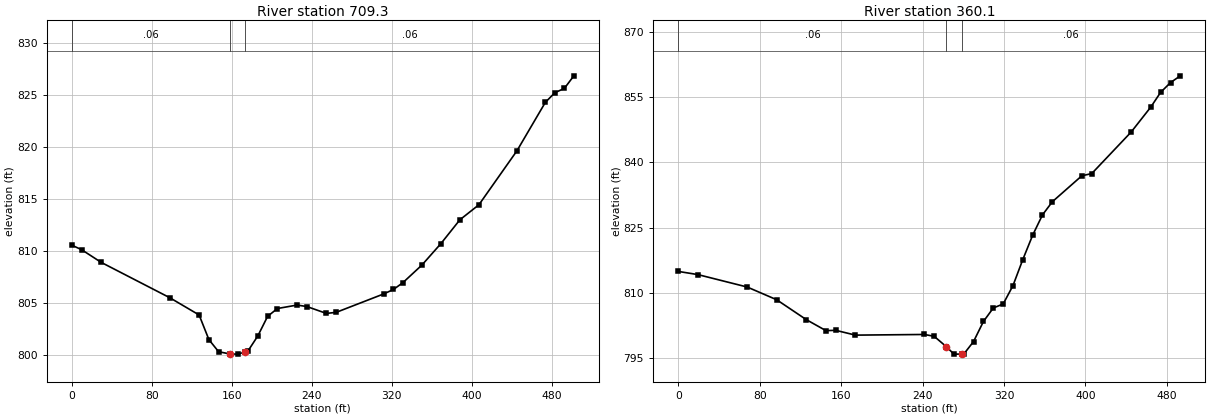
Type RM Length L Ch R = 1 ,709.3   ,332,348.1,364.2
XS GIS Cut Line= 3
     1698003.022      351479.151     1698240.444      351616.153
     1698342.455      351819.812
#Sta/Elev= 30
       0  810.55     9.8  810.12    29.4   808.9    97.9  805.51   127.3  803.85
   137.1  801.48   146.8  800.32   158.5   800.1   166.4  800.09   173.5  800.31
   176.2   800.4     186  801.84   195.8  803.72   205.6  804.47   225.2   804.8
     235  804.66   254.5     804   264.3   804.1   312.1  805.88   321.6   806.3
   331.1  806.96     350  808.64     369   810.7     388  812.99     407  814.43
     445  819.61   473.4  824.26   482.9  825.19   492.4   825.6   501.9  826.81
#Mann= 3 , 0 , 0
       0     .06       0   158.5    .045       0   173.5     .06       0
Bank Sta=158.5,173.5
XS Rating Curve= 0 ,0
Exp/Cntr=0.3,0.1

Type RM Length L Ch R = 1 ,360.1   ,358.6,360.1,361.5
XS GIS Cut Line= 2
     1697918.678      351564.444     1698076.766       352031.65
#Sta/Elev= 30
       0  814.97    19.3  814.24    67.7  811.39    96.7  808.47   125.7  803.92
   145.1  801.38   154.7  801.45   174.1  800.35   241.8   800.5   251.4  800.08
   263.5  797.67   270.8  795.99   278.5     796   280.5     796   290.1  798.88
   299.8  803.48   309.5  806.58   319.2   807.5   328.8   811.7   338.5   817.7
   348.2   823.3   357.8  827.94   367.5  830.96   396.5  836.92   406.2  837.42
   444.9  846.95   464.2  852.68   473.9  856.07   483.6   858.3   493.2  859.85
#Mann= 3 , 0 , 0
       0     .06       0   263.5    .045       0   278.5     .06       0
Bank Sta=263.5,278.5
XS Rating Curve= 0 ,0
Exp/Cntr=0.3,0.1

Chan Stop Cuts=-1
Use User Specified Reach Order=0
Composite Channel Slope=5